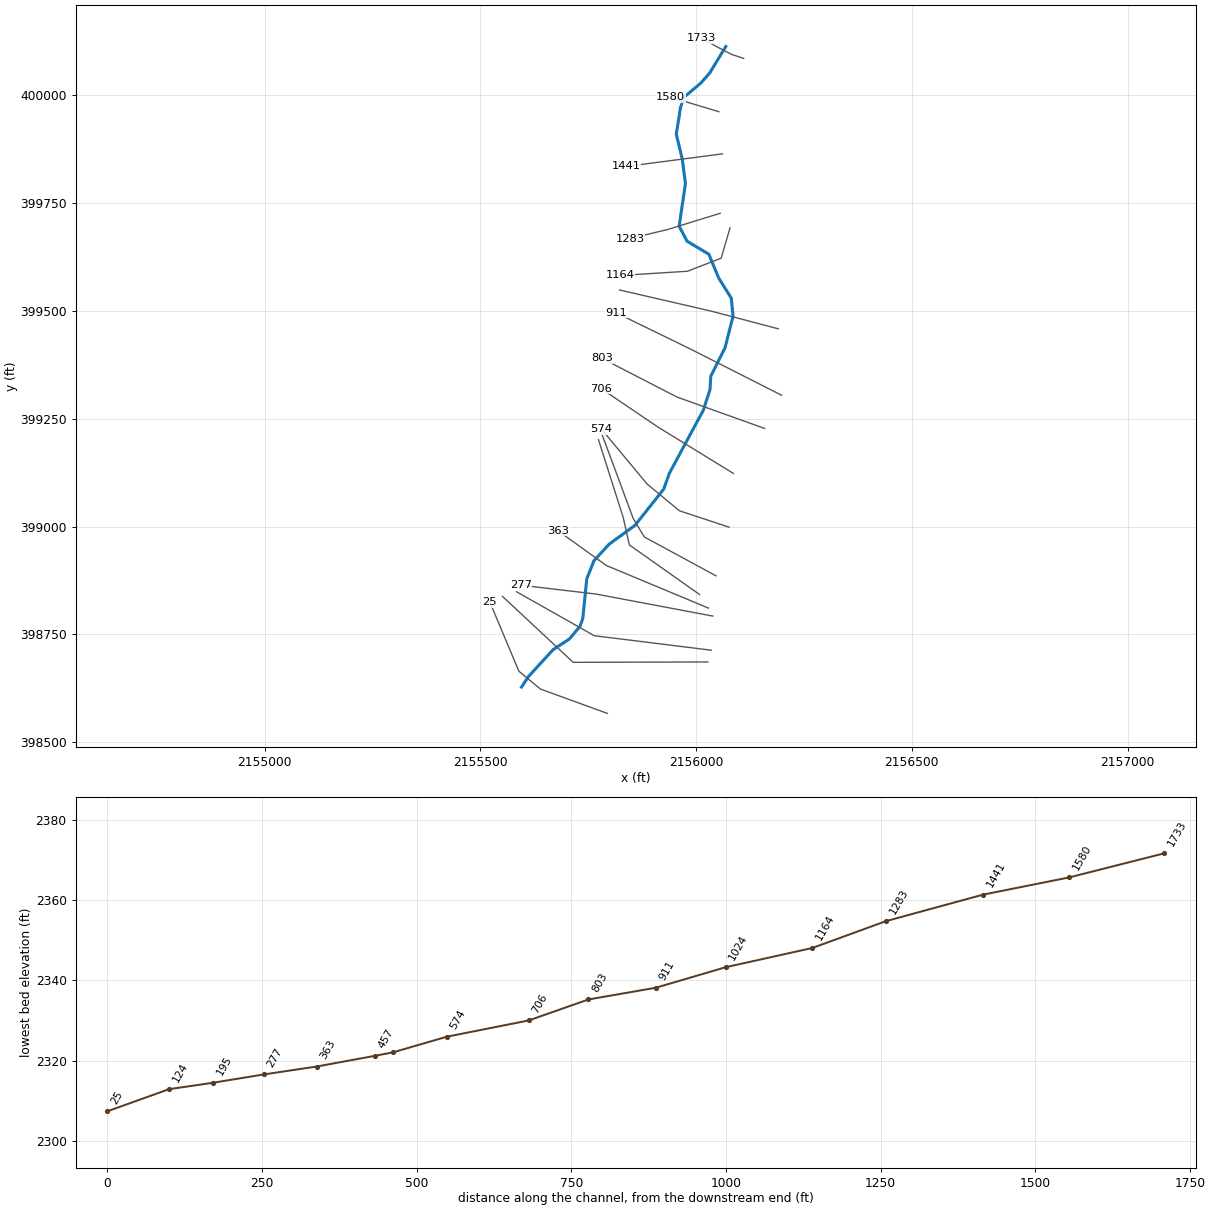
--- BOGGSRN.prj (project) ---

Proj Title=BOGGSRN
Current Plan=p01
Default Exp/Contr=0.3,0.1
English Units
Geom File=g01
Flow File=f01
Plan File=p01
Y Axis Title=Elevation
X Axis Title(PF)=Main Channel Distance
X Axis Title(XS)=Station
BEGIN DESCRIPTION:
Stream Name- Boggs Run
Flood Zone: Zone A
Greenbrier County, WV
County-Wide Study
WVDHSEM-2018-3, Flood Risk Project
HEC-RAS Version: 5.0.7
General Notes:
For the Hydrology Regression was used.
END DESCRIPTION:
DSS Export Rating Curves= 0
DSS Export Rating Curve Sorted= 0
DSS Export Volume Flow Curves= 0
DXF Filename=A3a.
DXF OffsetX= 0
DXF OffsetY= 0
DXF ScaleX= 1
DXF ScaleY= 10

--- BOGGSRN.p01 (plan) ---

Plan Title=Floodplain
Program Version=5.07
Short Identifier=Floodplain
Geom File=g01
Flow File=f01
Subcritical Flow
K Sum by GR= 0
Std Step Tol= 0.01
Critical Tol= 0.01
Num of Std Step Trials= 20
Max Error Tol= 0.3
Flow Tol Ratio= 0.001
Split Flow NTrial= 30
Split Flow Tol= 0.02
Split Flow Ratio= 0.02
Log Output Level= 0
Friction Slope Method= 1
Unsteady Friction Slope Method= 2
Unsteady Bridges Friction Slope Method= 1
Parabolic Critical Depth
Global Vel Dist= 0 , 0 , 0
Global Log Level= 0
CheckData=True
Encroach Param=-1 ,0,0, 0
Computation Interval=1MIN
Output Interval=1HOUR
Instantaneous Interval=1HOUR
Mapping Interval=1HOUR
Computation Time Step Use Courant=        0
Computation Time Step Use Time Series=    0
Computation Time Step Count To Double=0
Computation Time Step Max Doubling=0
Computation Time Step Max Halving=0
Computation Time Step Residence Courant=0
Run HTab= 0
Run UNet= 0
Run Sediment= 0
Run PostProcess= 0
Run WQNet= 0
Run RASMapper= 0
UNET Theta= 1
UNET Theta Warmup= 1
UNET ZTol= 0.02
UNET ZSATol= 0.02
UNET MxIter= 20
UNET Max Iter WO Improvement= 0
UNET MaxInSteps= 0
UNET DtIC= 0
UNET DtMin= 0
UNET MaxCRTS= 20
UNET WFStab= 2
UNET SFStab= 1
UNET WFX= 1
UNET SFX= 1
UNET 1D Methodology=Finite Difference
UNET DSS MLevel= 4
UNET Pardiso=0
UNET DZMax Abort= 100
UNET Use Existing IB Tables=-1
UNET Froude Reduction=False
UNET Froude Limit= 0.8
UNET Froude Power= 4
UNET D1 Cores= 0
UNET D2 Coriolis=0
UNET D2 Cores= 0
UNET D2 Theta= 1
UNET D2 Theta Warmup= 1
UNET D2 Z Tol= 0.01
UNET D2 Volume Tol= 0.01
UNET D2 Max Iterations= 20
UNET D2 Equation= 0
UNET D2 RampUpFraction=0.1
UNET D2 TimeSlices= 1
UNET D2 BCVolumeCheck=0
UNET D1D2 MaxIter= 0
UNET D1D2 ZTol=0.01
UNET D1D2 QTol=0.1
UNET D1D2 MinQTol=1
Write IC File= 0
Write IC File at Fixed DateTime=0
Write IC File at Sim End=0
Echo Input=False
Echo Parameters=False
Echo Output=False
Write Detailed= 0
HDF Write Warmup=0
HDF Write Time Slices=0
HDF Flush=0
HDF Face Node Velocities=0
HDF Compression= 1
HDF Chunk Size= 1
HDF Spatial Parts= 1
HDF Use Max Rows=0
HDF Fixed Rows= 1
Calibration Method= 0
Calibration Iterations= 20
Calibration Max Change=0.05
Calibration Tolerance=0.2
Calibration Maximum=1.5
Calibration Minimum=0.5
Calibration Optimization Method= 1
WQ AD Non Conservative
WQ ULTIMATE=-1
WQ Max Comp Step=1HOUR
WQ Output Interval=15MIN
WQ Output Selected Increments= 0
WQ Output face flow=0
WQ Output face velocity=0
WQ Output face area=0
WQ Output face dispersion=0
WQ Output cell volume=0
WQ Output cell surface area=0
WQ Output cell continuity=0
WQ Output cumulative cell continuity=0
WQ Output face conc=0
WQ Output face dconc_dx=0
WQ Output face courant=0
WQ Output face peclet=0
WQ Output face adv mass=0
WQ Output face disp mass=0
WQ Output cell mass=0
WQ Output cell source sink temp=0
WQ Output nsm pathways=0
WQ Output nsm derived pathways=0
WQ Output MaxMinRange=-1
WQ Daily Max Min Mean=-1
WQ Daily Range=0
WQ Daily Time=0
WQ Create Restart=0
WQ Fixed Restart=0
WQ System Summary=0
WQ Write To DSS=0
WQ Use Fixed Temperature=0
Sorting and Armoring Iterations= 10
XS Update Threshold= 0.02
Bed Roughness Predictor= 0
Hydraulics Update Threshold= 0.02
Energy Slope Method= 1
Volume Change Method= 1
Sediment Retention Method= 0
XS Weighting Method= 0
Number of US Weighted Cross Sections= 1
Number of DS Weighted Cross Sections= 1
Upstream XS Weight=0
Main XS Weight=1
Downstream XS Weight=0
Number of DS XS's Weighted with US Boundary= 1
Upstream Boundary Weight= 1
Weight of XSs Associated with US Boundary= 0
Number of US XS's Weighted with DS Boundary= 1
Downstream Boundary Weight= 0.5
Weight of XSs Associated with DS Boundary= 0.5
Percentile Method= 0
Sediment Output Level= 3
Mass or Volume Output= 0
Output Increment Type= 1
Profile and TS Output Increment= 1
XS Output Flag= 0
XS Output Increment= 10
Write Gradation File= 0
Read Gradation Hotstart= 0
Write HDF5 File= 1
Write Binary Output= 1
Write DSS Sediment File= 0
SV Curve= 0
Specific Gage Flag= 0

--- BOGGSRN.f01 (steady flow) ---

Flow Title=Flow
Program Version=5.07
Number of Profiles= 6
Profile Names=f1p,f10p,f4p,f2p,f02p,f1pplus
River Rch & RM=BEVERLYFK,Main            ,776
     323     167     225     272     456     478
River Rch & RM=BEVERLYFK,Main            ,220
     537     283     377     454     751     794
River Rch & RM=BOGGSRN,Main            ,1733
     558     295     392     472     780     825
River Rch & RM=DRYRN,Main            ,9301
     532     280     373     450     744     787
River Rch & RM=DRYRN,Main            ,8316
     594     314     418     503     829     878
River Rch & RM=DRYRN,Main            ,6862
     769     411     544     653    1070    1140
River Rch & RM=DRYRN,Main            ,5213
     898     483     637     763    1240    1330
River Rch & RM=DRYRN,Main            ,259
    1110     604     793     948    1540    1650
River Rch & RM=PNTHRCMPCK,Main            ,14558
     513     270     359     434     718     758
River Rch & RM=PNTHRCMPCK,Main            ,13060
     599     317     422     508     836     886
River Rch & RM=PNTHRCMPCK,Main            ,10150
     873     469     619     742    1210    1290
River Rch & RM=PNTHRCMPCK,Main            ,8160
     976     526     693     830    1350    1440
River Rch & RM=PNTHRCMPCK,Main            ,6420
    1080     588     772     923    1500    1600
River Rch & RM=RCKCMPRN,Main            ,4355
     581     307     409     492     812     860
River Rch & RM=RCKCMPRN,Main            ,1618
     692     368     488     586     963    1020
River Rch & RM=ROBBINSRN,Main            ,27789
     907     488     643     771    1260    1340
River Rch & RM=ROBBINSRN,Main            ,27014
    1170     638     837    1000    1620    1740
River Rch & RM=ROBBINSRN,Main            ,21785
    1330     728     953    1140    1830    1970
River Rch & RM=ROBBINSRN,Main            ,16781
    1830    1010    1320    1570    2500    2710
River Rch & RM=ROBBINSRN,Main            ,10962
    2050    1140    1480    1750    2790    3030
River Rch & RM=SPRINGCKT3,Main            ,6529
     583     309     410     494     815     863
River Rch & RM=SPRINGCKT3,Main            ,3093
     683     363     482     579     951    1010
River Rch & RM=SPRINGCKT3,Main            ,434
     860     462     609     730    1190    1270
Boundary for River Rch & Prof#=BEVERLYFK,Main            , 1
Up Type= 0
Dn Type= 3
Dn Slope=0.045649
Boundary for River Rch & Prof#=BEVERLYFK,Main            , 2
Up Type= 0
Dn Type= 3
Dn Slope=0.045649
Boundary for River Rch & Prof#=BEVERLYFK,Main            , 3
Up Type= 0
Dn Type= 3
Dn Slope=0.045649
Boundary for River Rch & Prof#=BEVERLYFK,Main            , 4
Up Type= 0
Dn Type= 3
Dn Slope=0.045649
Boundary for River Rch & Prof#=BEVERLYFK,Main            , 5
Up Type= 0
Dn Type= 3
Dn Slope=0.045649
Boundary for River Rch & Prof#=BEVERLYFK,Main            , 6
Up Type= 0
Dn Type= 3
Dn Slope=0.045649
Boundary for River Rch & Prof#=BOGGSRN,Main            , 1
Up Type= 0
Dn Type= 3
Dn Slope=0.043074
Boundary for River Rch & Prof#=BOGGSRN,Main            , 2
Up Type= 0
Dn Type= 3
Dn Slope=0.043074
Boundary for River Rch & Prof#=BOGGSRN,Main            , 3
Up Type= 0
Dn Type= 3
Dn Slope=0.043074
Boundary for River Rch & Prof#=BOGGSRN,Main            , 4
Up Type= 0
Dn Type= 3
Dn Slope=0.043074
Boundary for River Rch & Prof#=BOGGSRN,Main            , 5
Up Type= 0
Dn Type= 3
Dn Slope=0.043074
Boundary for River Rch & Prof#=BOGGSRN,Main            , 6
Up Type= 0
Dn Type= 3
Dn Slope=0.043074
Boundary for River Rch & Prof#=DRYRN,Main            , 1
Up Type= 0
Dn Type= 3
Dn Slope=0.021282
Boundary for River Rch & Prof#=DRYRN,Main            , 2
Up Type= 0
Dn Type= 3
Dn Slope=0.021282
Boundary for River Rch & Prof#=DRYRN,Main            , 3
Up Type= 0
Dn Type= 3
Dn Slope=0.021282
Boundary for River Rch & Prof#=DRYRN,Main            , 4
Up Type= 0
Dn Type= 3
Dn Slope=0.021282
Boundary for River Rch & Prof#=DRYRN,Main            , 5
Up Type= 0
Dn Type= 3
Dn Slope=0.021282
Boundary for River Rch & Prof#=DRYRN,Main            , 6
Up Type= 0
Dn Type= 3
Dn Slope=0.021282
Boundary for River Rch & Prof#=PNTHRCMPCK,Main            , 1
Up Type= 0
Dn Type= 3
Dn Slope=0.02712
Boundary for River Rch & Prof#=PNTHRCMPCK,Main            , 2
Up Type= 0
Dn Type= 3
Dn Slope=0.02712
Boundary for River Rch & Prof#=PNTHRCMPCK,Main            , 3
Up Type= 0
Dn Type= 3
Dn Slope=0.02712
Boundary for River Rch & Prof#=PNTHRCMPCK,Main            , 4
Up Type= 0
Dn Type= 3
Dn Slope=0.02712
Boundary for River Rch & Prof#=PNTHRCMPCK,Main            , 5
Up Type= 0
Dn Type= 3
Dn Slope=0.02712
Boundary for River Rch & Prof#=PNTHRCMPCK,Main            , 6
Up Type= 0
Dn Type= 3
Dn Slope=0.02712
Boundary for River Rch & Prof#=RCKCMPRN,Main            , 1
Up Type= 0
Dn Type= 3
Dn Slope=0.013802
Boundary for River Rch & Prof#=RCKCMPRN,Main            , 2
Up Type= 0
Dn Type= 3
Dn Slope=0.013802
Boundary for River Rch & Prof#=RCKCMPRN,Main            , 3
Up Type= 0
Dn Type= 3
Dn Slope=0.013802
Boundary for River Rch & Prof#=RCKCMPRN,Main            , 4
Up Type= 0
Dn Type= 3
Dn Slope=0.013802
Boundary for River Rch & Prof#=RCKCMPRN,Main            , 5
Up Type= 0
Dn Type= 3
Dn Slope=0.013802
Boundary for River Rch & Prof#=RCKCMPRN,Main            , 6
Up Type= 0
Dn Type= 3
Dn Slope=0.013802
Boundary for River Rch & Prof#=ROBBINSRN,Main            , 1
Up Type= 0
Dn Type= 3
Dn Slope=0.010317
Boundary for River Rch & Prof#=ROBBINSRN,Main            , 2
Up Type= 0
Dn Type= 3
Dn Slope=0.010317
Boundary for River Rch & Prof#=ROBBINSRN,Main            , 3
Up Type= 0
Dn Type= 3
Dn Slope=0.010317
Boundary for River Rch & Prof#=ROBBINSRN,Main            , 4
Up Type= 0
Dn Type= 3
Dn Slope=0.010317
Boundary for River Rch & Prof#=ROBBINSRN,Main            , 5
Up Type= 0
Dn Type= 3
Dn Slope=0.010317
Boundary for River Rch & Prof#=ROBBINSRN,Main            , 6
Up Type= 0
Dn Type= 3
Dn Slope=0.010317
Boundary for River Rch & Prof#=SPRINGCKT3,Main            , 1
Up Type= 0
Dn Type= 3
Dn Slope=0.016207
Boundary for River Rch & Prof#=SPRINGCKT3,Main            , 2
Up Type= 0
Dn Type= 3
Dn Slope=0.016207
Boundary for River Rch & Prof#=SPRINGCKT3,Main            , 3
Up Type= 0
Dn Type= 3
Dn Slope=0.016207
Boundary for River Rch & Prof#=SPRINGCKT3,Main            , 4
Up Type= 0
Dn Type= 3
Dn Slope=0.016207
Boundary for River Rch & Prof#=SPRINGCKT3,Main            , 5
Up Type= 0
Dn Type= 3
Dn Slope=0.016207
Boundary for River Rch & Prof#=SPRINGCKT3,Main            , 6
Up Type= 0
Dn Type= 3
Dn Slope=0.016207
DSS Import GetInterval= 0
DSS Import GetPeak= 0
DSS Import FillOption= 0

--- BOGGSRN.g01 (geometry) ---

Geom Title=Geometry
Program Version=5.07

River Reach=BOGGSRN         ,Main
Reach XY= 30
2156068.97058138400113.5331687332156031.99165273400052.626138315
2156012.00875306 400029.604858892155972.20502688399995.998298809
2155964.19421613399972.7211143972155954.23754314399910.203522891
2155967.99112456399853.1111173932155975.50128014399795.629276976
2155960.89008889399696.8364955632155979.26242746399661.918914482
2156029.65307473399631.9222553072156052.60545664399576.464032888
 2156081.6651098399530.0540207332156085.81175506 399487.92746456
2156067.10969272399414.5680312222156034.30660872399349.234828562
2156032.36566772399317.9478176392156016.73873048 399269.59883298
2155938.45115739399124.3264857232155925.11325756399087.012583971
2155858.63865297399003.090179637 2155798.8467778 398959.43803598
2155763.49218972398921.0532702212155746.81505772 398878.95427306
2155737.64512855398787.103078812 2155731.2288028398768.893141478
2155706.67143722398739.4998275642155668.94677514  398714.8417404
 2155610.7231383398651.2188361442155595.68018939398627.858646646

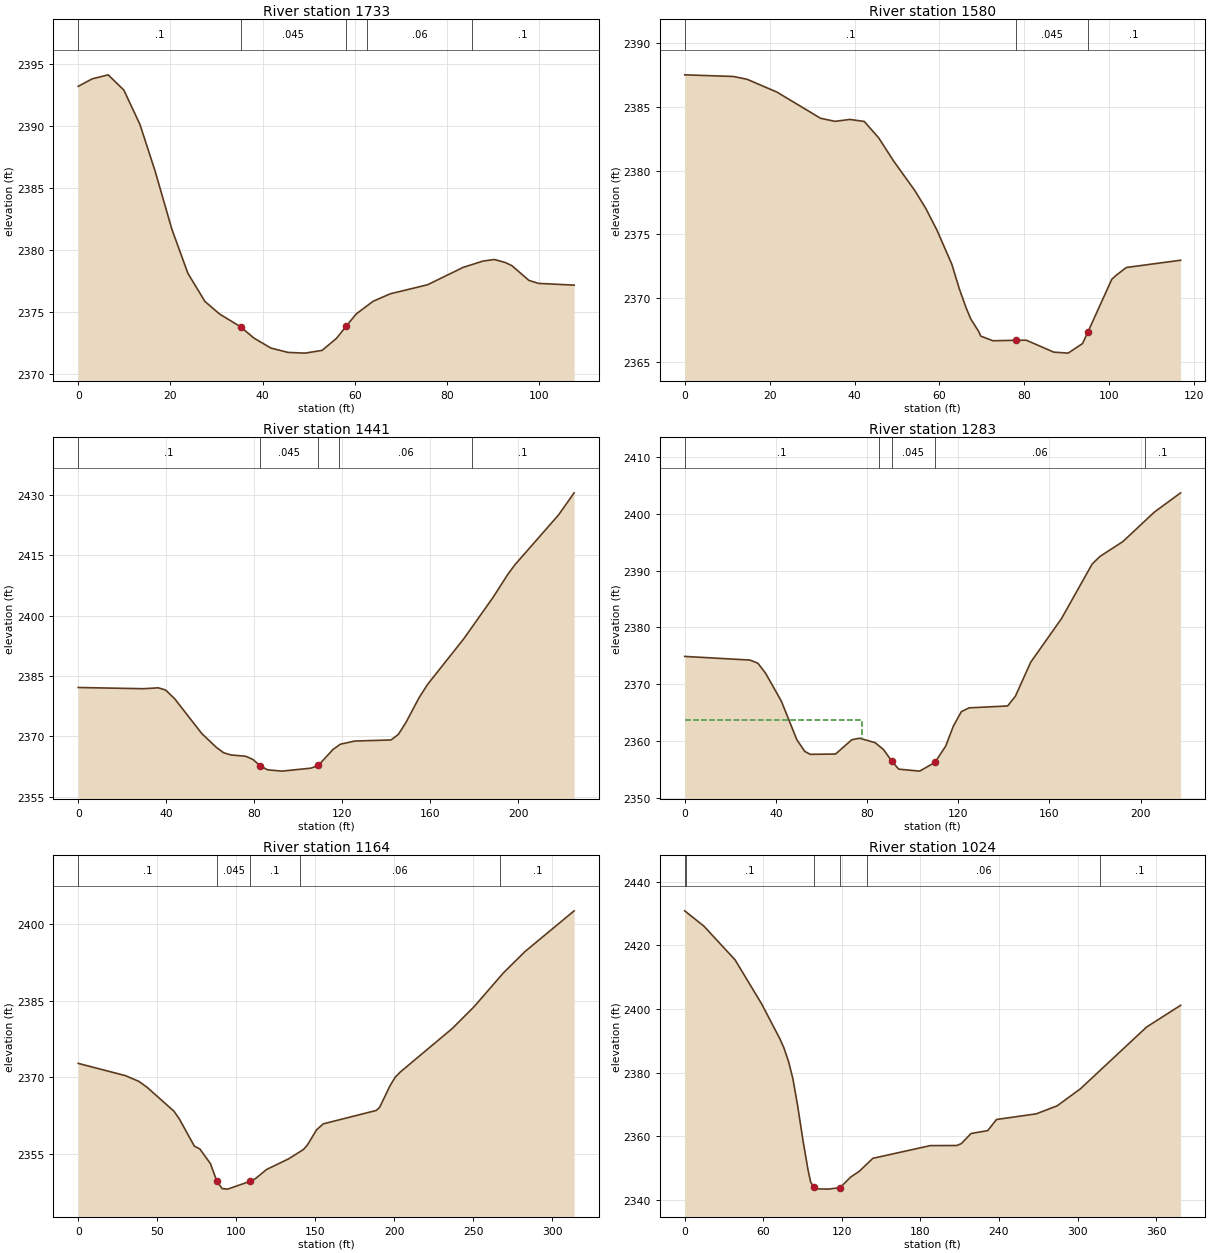
Type RM Length L Ch R = 1 ,1733    ,152.3,153.4,154.1
XS GIS Cut Line= 5
2156110.34090547400085.9935256392156082.32488538400095.328808814
 2156064.5785298400104.5515593892156046.83184613400113.774638057
2156013.65508954400132.527394187
#Sta/Elev= 30
       0  2393.2       3  2393.8     6.5 2394.13     9.9  2392.9    13.4 2390.12
    16.7 2386.34    20.3 2381.69    23.8  2378.1    27.5 2375.83    30.7 2374.81
   35.242373.786    38.1 2372.88    41.8 2372.07    45.5 2371.72    49.2 2371.66
    52.9 2371.88      56 2372.84    58.1 2373.81    60.3 2374.82      64 2375.85
    67.7 2376.45    75.8 2377.18    83.5 2378.58    87.8 2379.09    90.3 2379.22
    92.7 2378.97    94.1 2378.72    97.8 2377.53    99.9 2377.29   107.6 2377.15
#Mann= 5 ,-1 , 0
       0      .1       0   35.24    .045       0    58.1      .1       0
   62.61     .06       0   85.42      .1       0
Bank Sta=35.24,58.1
XS Rating Curve= 0 ,0
Exp/Cntr=0.3,0.1

Type RM Length L Ch R = 1 ,1580    ,134.3,138.9,143
XS GIS Cut Line= 2
2156052.83216222399962.2956103092155941.07567918399996.171932129
#Sta/Elev= 30
       0 2387.51    11.5 2387.38    14.7 2387.16    21.7 2386.16      32  2384.1
    35.4 2383.86    38.9 2384.01    42.3 2383.85    45.7 2382.56    49.2 2380.75
    54.2 2378.43    56.8 2377.02    59.4 2375.33    62.9 2372.66    64.7  2370.7
    66.3 2369.21    67.4 2368.34    69.3 2367.34    69.7 2367.01    72.6 2366.64
   78.112366.681    80.5 2366.68    86.9 2365.75    90.3 2365.67    93.7 2366.42
   94.942367.312   100.6 2371.47   101.6 2371.77     104 2372.39   116.8 2372.96
#Mann= 3 ,-1 , 0
       0      .1       0   78.11    .045       0   94.94      .1       0
Bank Sta=78.11,94.94
XS Rating Curve= 0 ,0
Exp/Cntr=0.3,0.1

Type RM Length L Ch R = 1 ,1441    ,156.1,157.2,157.7
XS GIS Cut Line= 2
2156061.51291914399864.6393095552155837.98843181399835.342452139
#Sta/Elev= 30
       0 2382.18    29.7 2381.88    36.4  2382.1    39.7 2381.56    43.8 2379.41
    56.2 2370.71    62.8 2367.29    66.1 2365.96    69.4 2365.41    76.1 2365.09
    79.4 2364.29    82.7 2362.73      86 2361.72    92.6 2361.39   105.8 2362.13
   109.1  2362.8   115.8 2366.77   119.1 2368.08   125.7 2368.87   142.2 2369.14
   145.5 2370.52   148.9 2373.43   154.9 2379.63   158.8 2382.96   175.2 2394.27
   188.6 2404.63   195.2 2410.27   198.5 2412.71   218.3 2425.08   225.4 2430.58
#Mann= 5 ,-1 , 0
       0      .1       0    82.7    .045       0   109.1      .1       0
  118.38     .06       0  179.11      .1       0
Bank Sta=82.7,109.1
XS Rating Curve= 0 ,0
Exp/Cntr=0.3,0.1

Type RM Length L Ch R = 1 ,1283    ,117.2,119.1,116.9
XS GIS Cut Line= 3
2156056.08740506399726.835451305 2155933.4744613399688.857836977
2155846.66918872399668.241736472
#Sta/Elev= 30
       0 2374.92    28.6 2374.28    32.1 2373.73    35.5 2371.97    42.4 2367.08
    49.2 2360.31    52.7 2358.24    55.1 2357.73    66.2 2357.78    73.3 2360.28
    76.7 2360.56    83.6 2359.77    87.3 2358.54   90.912356.517    93.9 2355.13
   103.1 2354.78   109.82356.309   114.5 2359.15   117.9 2362.69   121.4 2365.23
   124.8 2365.89   141.7 2366.22   145.1 2367.93   151.8 2373.88   165.3 2381.54
   178.8 2391.15   182.2 2392.47   192.3 2395.09     206 2400.23   217.6 2403.64
#Mann= 5 ,-1 , 0
       0      .1       0   85.21     .06       0   90.91    .045       0
   109.8     .06       0  202.01      .1       0
#XS Ineff= 2 , 0
           77.96 2363.79
Permanent Ineff=
       F       F
Bank Sta=90.91,109.8
XS Rating Curve= 0 ,0
Exp/Cntr=0.3,0.1

Type RM Length L Ch R = 1 ,1164    ,146.3,140.1,133.8
XS GIS Cut Line= 4
2156078.87377681399693.198379472 2156058.2576763399622.668664888
2155980.13250446399592.2868358942155823.88248889399582.521107391
#Sta/Elev= 30
       0 2372.71    29.8 2370.32    38.3  2369.2    43.5 2368.05    60.6 2363.35
      64 2361.84    73.5 2356.51      77 2355.95    83.7 2353.08    87.62349.759
    91.1 2348.19    94.6 2348.09  108.952349.641   112.2 2350.15   119.2 2351.93
   133.3 2354.04   142.5 2355.84     145  2356.7   150.9 2359.71   155.1 2360.87
   188.7  2363.5   190.8 2364.11   197.3  2368.3   200.6 2369.98   203.9 2371.03
   236.8 2379.55   250.6 2383.82   269.1 2390.42   282.8 2394.61   313.9 2402.58
#Mann= 5 ,-1 , 0
       0      .1       0    87.6    .045       0  108.95      .1       0
  140.23     .06       0   267.2      .1       0
Bank Sta=87.6,108.95
XS Rating Curve= 0 ,0
Exp/Cntr=0.3,0.1

Type RM Length L Ch R = 1 ,1024    ,116.4,113.1,111.6
XS GIS Cut Line= 3
2156190.63602047 399458.823192062156034.38600488399500.056049228
 2155822.7975173399548.884035558
#Sta/Elev= 30
       0 2430.91    14.7 2426.09    38.5 2415.47    58.8 2401.59    72.7 2390.62
    75.8 2387.74    79.2 2383.64    82.6 2378.12    86.1 2369.97    90.4 2358.49
    94.1 2349.55    96.2 2345.52   98.562343.981    99.6 2343.38   109.7  2343.3
  118.692343.776   126.7 2347.08   133.5 2348.97   143.7    2353   187.6    2357
   207.8 2357.03   211.2 2357.62   218.7 2360.81   231.4 2361.72   238.1 2365.22
   268.4 2366.99   284.4 2369.52   302.1 2374.85   352.7 2394.32   378.7 2401.17
#Mann= 6 ,-1 , 0
       0      .1       0     .88      .1       0   98.56    .045       0
  118.69      .1       0   139.5     .06       0  316.93      .1       0
Bank Sta=98.56,118.69
XS Rating Curve= 0 ,0
Exp/Cntr=0.3,0.1

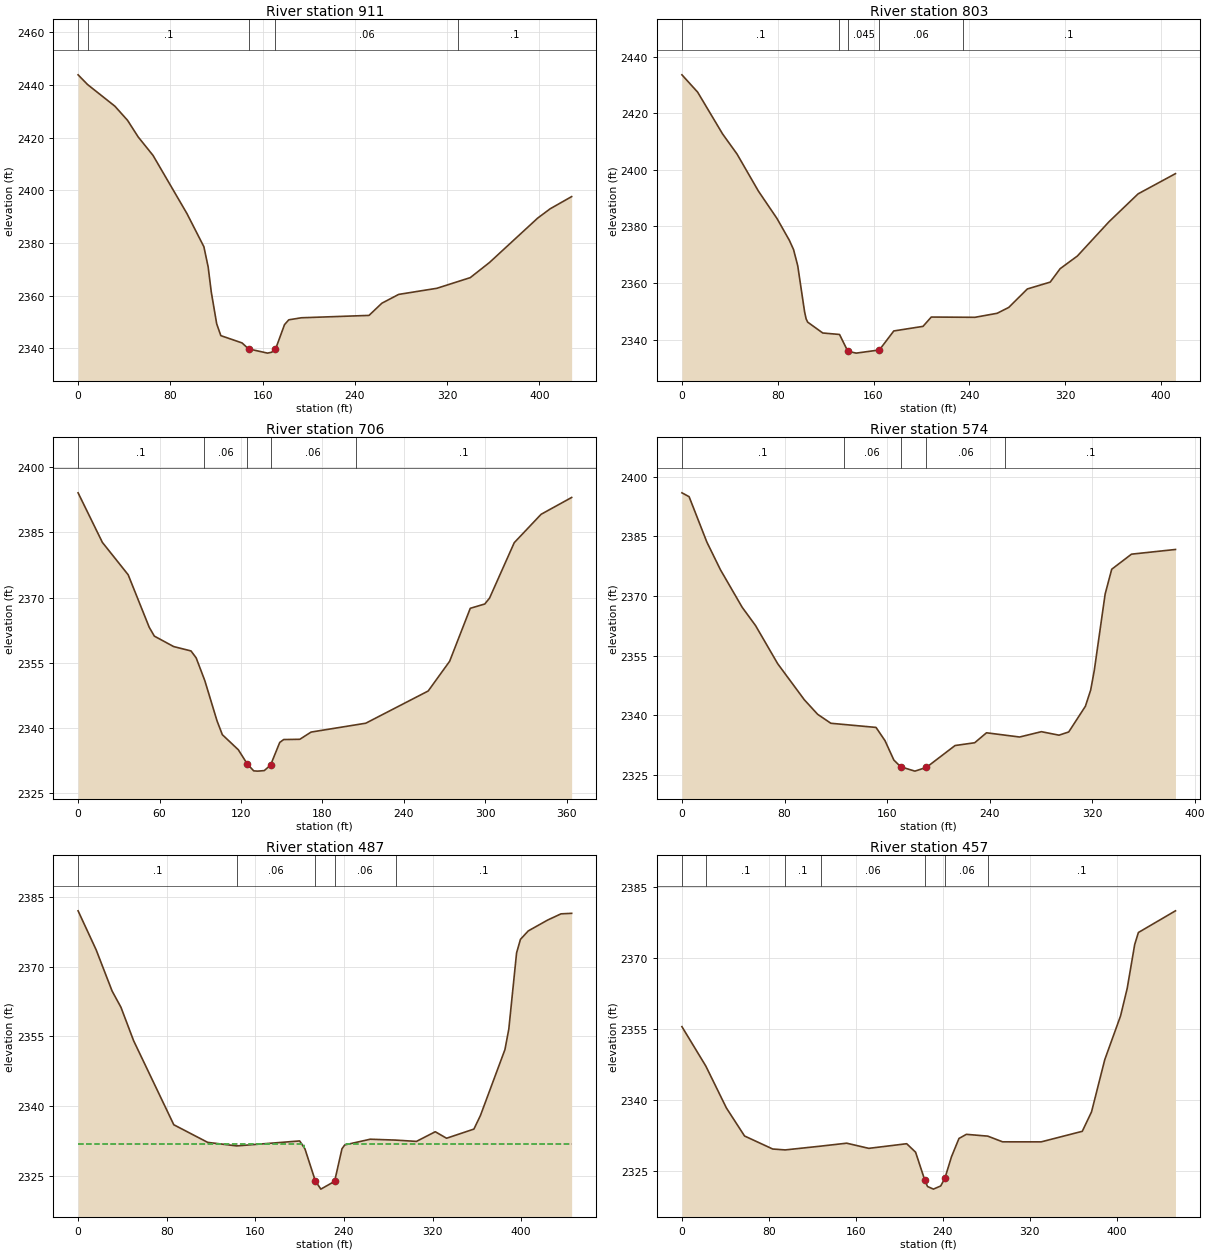
Type RM Length L Ch R = 1 ,911     ,105.6,108.6,108.7
XS GIS Cut Line= 3
2156198.23147772399304.7434477212155986.64299014399412.165148899
2155815.20206006399495.715506732
#Sta/Elev= 30
       0 2443.83     8.2 2440.15    31.9 2431.93    42.9 2426.55    52.1 2420.26
      65 2413.23    94.4 2391.16   109.1 2378.56   112.8 2370.88   115.5 2361.39
   120.2 2349.28   123.8 2344.82   142.2 2342.05   147.82339.792   164.3 2338.18
     168 2338.54  170.792339.819   171.7 2340.27     179 2348.99   182.7 2350.82
   193.6  2351.6   252.3  2352.5   263.4 2357.12     278 2360.47   311.2  2362.8
   340.1 2366.84   356.7 2372.56   398.5 2389.42   409.4 2392.98     428  2397.6
#Mann= 5 ,-1 , 0
       0      .1       0    8.97      .1       0   147.8    .045       0
  170.79     .06       0  329.72      .1       0
Bank Sta=147.8,170.79
XS Rating Curve= 0 ,0
Exp/Cntr=0.3,0.1

Type RM Length L Ch R = 1 ,803     ,98.6,96.7,93.8
XS GIS Cut Line= 3
2156159.16921988399227.7035755662155956.26116113399300.403233305
2155781.56498823399390.463748723
#Sta/Elev= 30
       0 2433.56    13.1 2427.46      34 2412.65      46 2405.59    63.9 2392.47
    79.4 2382.81    89.7 2375.12    93.2 2371.85    96.7 2366.14   102.4 2349.93
   103.7 2347.38     105 2346.22   117.6 2342.38   131.6 2341.86   138.5 2335.95
   145.5 2335.27  164.87 2336.39   176.9  2343.1   201.3 2344.72   208.2 2348.01
   244.7 2347.92   263.2 2349.34   272.9 2351.41   288.4 2357.93   307.5 2360.35
   315.8 2365.09   330.2 2369.57   356.6 2381.67   380.9 2391.52   412.1 2398.66
#Mann= 5 ,-1 , 0
       0      .1       0  131.14     .06       0   138.5    .045       0
  164.87     .06       0  234.56      .1       0
Bank Sta=138.5,164.87
XS Rating Curve= 0 ,0
Exp/Cntr=0.3,0.1

Type RM Length L Ch R = 1 ,706     ,133.9,132.3,130.7
XS GIS Cut Line= 3
2156086.46956214399123.5367891492155911.77338922399230.958818391
2155780.47968856399319.934362233
#Sta/Elev= 30
       0 2394.11    17.9  2382.7    36.9 2375.25    52.4 2363.17    56.2 2361.12
    70.4 2358.72    83.2 2357.71      87 2356.12    93.4 2350.86   102.4  2341.6
   106.3 2338.43   118.1 2334.95  124.632331.714   129.4  2330.1   132.4 2330.04
   137.2 2330.16  141.862331.439   148.6 2336.65   151.5 2337.31   163.4 2337.37
   171.7 2339.03     212 2341.07     258 2348.49   273.8 2355.33     289 2367.52
   299.7 2368.52   303.2 2369.87   321.4 2382.63   341.2 2389.17   363.7 2393.04
#Mann= 5 ,-1 , 0
       0      .1       0   92.78     .06       0  124.63    .045       0
  141.86     .06       0  204.72      .1       0
Bank Sta=124.63,141.86
XS Rating Curve= 0 ,0
Exp/Cntr=0.3,0.1

Type RM Length L Ch R = 1 ,574     ,90.4,86.9,84.8
XS GIS Cut Line= 4
2156076.70383364398998.7539022272155961.68634714399036.731188476
2155886.81674622399098.5801461492155780.47968856399226.618275896
#Sta/Elev= 30
       0  2395.9     5.6 2394.93    19.4 2383.56      30 2376.59      47 2367.13
    57.4 2362.55    74.7 2352.95    95.4 2343.92   105.8 2340.26   116.1 2338.01
   151.3 2336.97   158.3 2333.64   165.2 2328.77  170.582327.067   181.6 2325.99
  190.582326.933   212.9 2332.42   228.2 2333.12   237.4 2335.62   263.2 2334.56
   280.2  2335.9   293.9 2335.02   301.5 2335.83   314.5 2342.29   318.6 2346.35
   321.4 2351.24   329.9 2370.49     335  2376.7   350.4 2380.49   384.7 2381.67
#Mann= 5 ,-1 , 0
       0      .1       0  126.14     .06       0  170.58    .045       0
  190.58     .06       0  252.11      .1       0
Bank Sta=170.58,190.58
XS Rating Curve= 0 ,0
Exp/Cntr=0.5,0.3

Type RM Length L Ch R = 1 ,487     ,31.8,29.6,26
XS GIS Cut Line= 4
2156046.32200463398885.9066869772155880.30626056398975.967202395
2155854.26464596399019.370002732 2155782.6499598399212.512661055
#Sta/Elev= 30
       0 2381.99    16.3  2373.6    30.7 2364.73    38.7 2361.23    50.1 2354.05
    86.4 2335.95     117 2332.16   143.2  2331.4     200 2332.47   204.8 2330.75
  214.162323.863   219.1  2322.1  231.542323.771   238.2 2330.79   240.7 2331.61
   263.7 2332.84   286.7 2332.65   305.4 2332.37   322.4 2334.45   332.6 2333.05
   357.3 2335.02   363.2 2337.96   385.3 2352.13   388.8 2356.56   395.8 2372.93
   399.3 2375.85   406.3 2377.66   423.8    2380   435.9 2381.34   445.5 2381.45
#Mann= 5 ,-1 , 0
       0      .1       0   143.2     .06       0  214.16    .045       0
  231.54     .06       0   286.7      .1       0
#XS Ineff= 2 , 0
          204.16  2331.9   241.5          2331.9
Permanent Ineff=
       F       F
Bank Sta=214.16,231.54
XS Rating Curve= 0 ,0
Exp/Cntr=0.5,0.3

Type RM Length L Ch R = 1 ,457     ,87.6,93.9,101.4
XS GIS Cut Line= 4
 2156008.3443903 398842.503886642155845.58388905398957.521045059
2155831.47794613399020.4553023872155773.96953097399201.661960974
#Sta/Elev= 30
       0 2355.53      22  2347.2    40.9 2338.36    57.6 2332.44    83.5 2329.69
      95  2329.5   127.7  2330.3   151.5 2330.92   171.9 2329.83   206.7 2330.81
   214.9 2329.02  223.32 2323.14   225.9 2321.77   231.3 2321.22     238 2321.89
  241.812323.496   247.9 2328.05   254.8 2331.92   261.6 2332.79   281.3 2332.41
   294.9 2331.21   330.4  2331.2   368.2 2333.43   376.7 2337.53   388.9 2348.58
   403.4  2357.8   409.5  2363.6   416.4 2372.87   419.8 2375.41   453.9 2379.99
#Mann= 7 ,-1 , 0
       0      .1       0      22      .1       0      95      .1       0
   127.7     .06       0  223.32    .045       0  241.81     .06       0
   281.3      .1       0
Bank Sta=223.32,241.81
XS Rating Curve= 0 ,0
Exp/Cntr=0.5,0.3

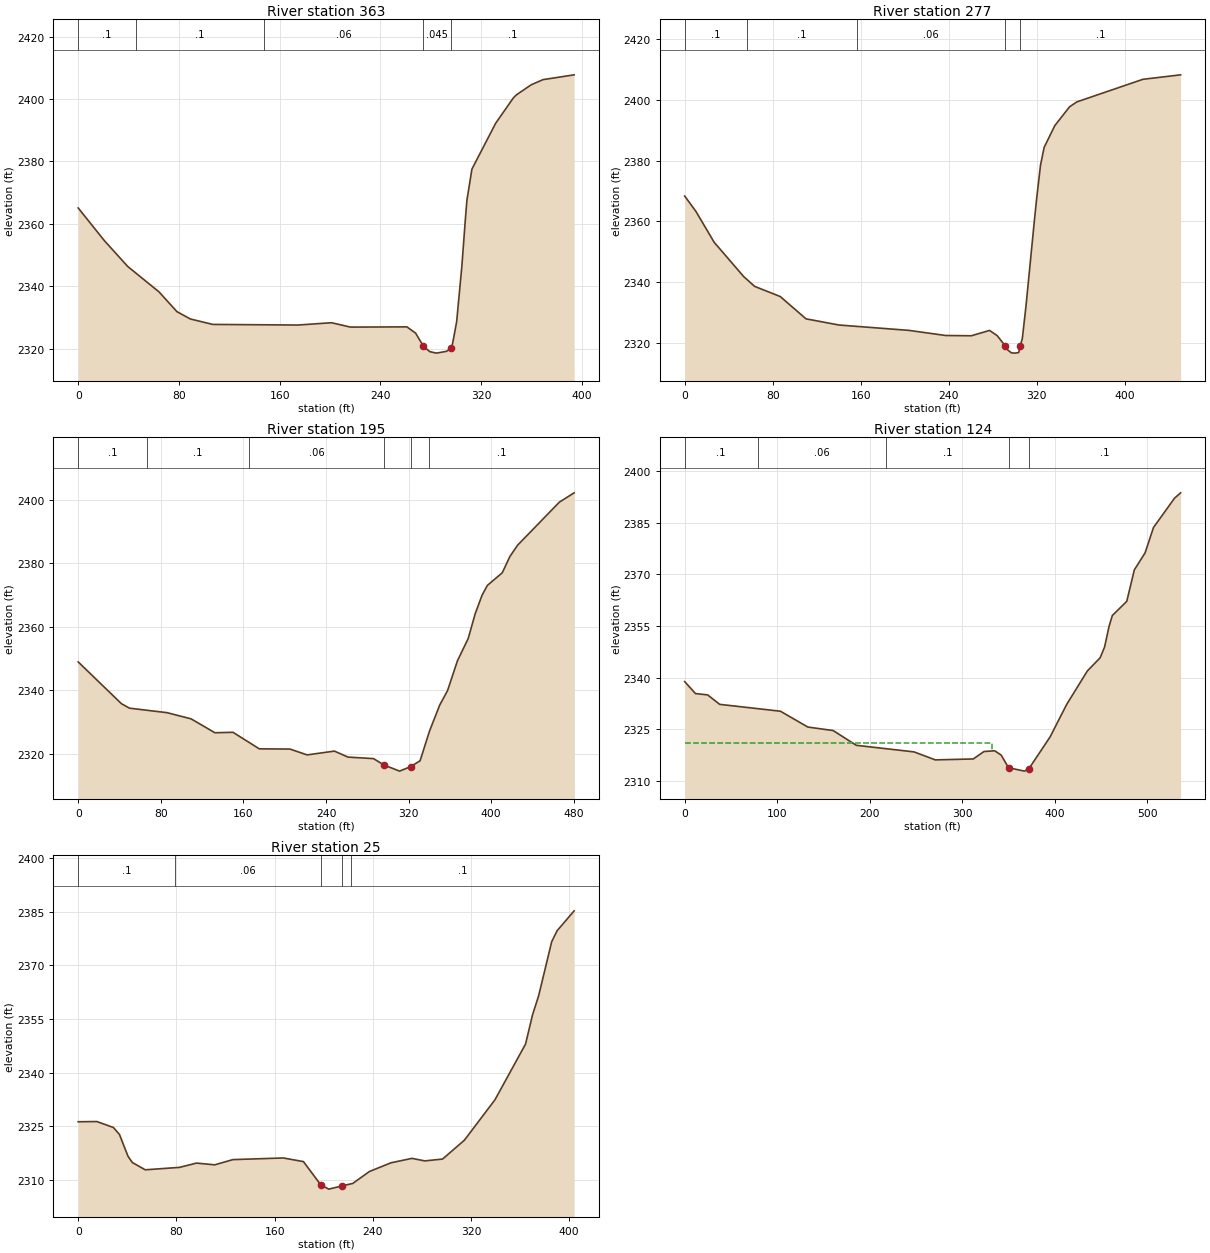
Type RM Length L Ch R = 1 ,363     ,80.1,85.9,90.1
XS GIS Cut Line= 3
2156028.96081889398811.0367579762155792.41568831398909.778030306
2155680.65344463398990.073145315
#Sta/Elev= 30
       0 2365.08    20.6 2354.69    39.3 2346.34    64.2 2338.18    78.4 2331.86
    89.1  2329.5   106.9 2327.76   174.4 2327.56   201.2  2328.3   216.3  2326.9
   261.1 2326.97     268 2324.96  274.142320.802   279.2 2319.04   284.5 2318.56
   292.5 2319.14  296.222320.128   296.6 2320.25   297.9 2322.78   300.6  2328.7
   304.7 2346.34   307.3 2360.42   308.7 2367.47   312.7 2377.52   331.6 2392.25
   345.7 2400.39   348.1 2401.34   359.8 2404.55   369.2  2406.2   393.9 2407.74
#Mann= 5 ,-1 , 0
       0      .1       0   45.61      .1       0  147.73     .06       0
  274.14    .045       0  296.22      .1       0
Bank Sta=274.14,296.22
XS Rating Curve= 0 ,0
Exp/Cntr=0.3,0.1

Type RM Length L Ch R = 1 ,277     ,88.6,82,78.6
XS GIS Cut Line= 3
2156038.72621931 398792.590600642155768.54401688398843.588858232
2155593.84784397398864.205286816
#Sta/Elev= 30
       0 2368.35    10.2  2363.3    26.8 2353.12    53.6 2341.83    63.6 2338.58
    86.9 2335.23   110.3 2327.88   140.4 2325.84   203.8 2324.08   237.2 2322.39
   260.6  2322.3   277.2 2324.06   284.1 2322.35  291.242319.081   293.7 2317.63
   297.1 2316.67   300.4 2316.58   303.7 2316.78  305.112318.925     307 2321.44
   310.3 2332.05   317.8 2359.72   320.2 2368.15   323.5 2378.48   326.8 2384.37
   336.5 2391.55   349.9 2397.75   356.5 2399.37   416.6 2406.82   450.9  2408.3
#Mann= 5 ,-1 , 0
       0      .1       0   56.97      .1       0  156.33     .06       0
  291.24    .045       0  305.11      .1       0
Bank Sta=291.24,305.11
XS Rating Curve= 0 ,0
Exp/Cntr=0.3,0.1

Type RM Length L Ch R = 1 ,195     ,74.7,70.8,68.4
XS GIS Cut Line= 3
2156035.47130455398713.3804572222155764.20380247398747.017857149
2155584.08211547398849.014372304
#Sta/Elev= 30
       0 2348.91    41.9 2335.74    49.7 2334.34    86.1 2332.92   109.3 2330.98
   132.4  2326.6   149.9 2326.74   175.4 2321.53   205.1 2321.46   221.7 2319.62
   248.1 2320.82   261.3 2318.93     286 2318.45  295.992316.473   311.2 2314.51
  321.862315.917   331.1 2317.77   340.2 2327.11   350.1 2335.31   357.7 2339.89
   367.3 2349.28   377.7 2356.29   384.4 2364.03   391.1 2369.91   396.2    2373
   410.7    2377     418 2382.08   425.5 2385.67     466 2399.25   480.3 2402.18
#Mann= 6 ,-1 , 0
       0      .1       0   66.47      .1       0  165.87     .06       0
  295.99    .045       0  321.86     .06       0   340.2      .1       0
Bank Sta=295.99,321.86
XS Rating Curve= 0 ,0
Exp/Cntr=0.3,0.1

Type RM Length L Ch R = 1 ,124     ,99.4,99.6,100.2
XS GIS Cut Line= 3
2156027.29189225398686.1428532042155715.34170528398685.281190446
2155551.53001522398838.163672224
#Sta/Elev= 30
       0 2338.89    11.7 2335.42    24.8 2335.04    37.9 2332.29   103.5  2330.3
   133.1 2325.71   160.5 2324.69   185.5 2320.41   247.9  2318.5   270.9 2316.18
   311.9 2316.45   323.5 2318.61   335.1 2318.82   342.1 2317.57     350 2313.91
   367.2 2312.92     372 2313.61   394.9 2322.83   412.8 2332.24   435.2 2341.98
     449  2345.8   453.8 2348.91   458.6 2354.85   462.2 2358.07   477.8 2362.18
     486 2371.32   497.6 2376.24   506.7 2383.61   529.5 2392.13     536 2393.66
#Mann= 5 ,-1 , 0
       0      .1       0   78.99     .06       0  217.56      .1       0
     350    .045       0     372      .1       0
#XS Ineff= 2 , 0
          331.81 2321.19
Permanent Ineff=
       F       F
Bank Sta=350,372
XS Rating Curve= 0 ,0
Exp/Cntr=0.3,0.1

Type RM Length L Ch R = 1 ,25      ,21.25,25,19.75
XS GIS Cut Line= 4
2155794.58563147398566.8961701392155639.42091556398623.319941804
2155589.50762956398664.552470893 2155522.2331578398825.142700896
#Sta/Elev= 30
       0 2326.25    15.2 2326.31    28.7 2324.64    33.6  2322.7    40.6 2316.58
    44.1 2314.86    54.6 2312.82    82.5  2313.5    96.4  2314.7   111.2 2314.21
     126 2315.67   167.1 2316.13   183.5 2315.11  197.482308.665   204.1 2307.42
  214.992308.314   223.7 2309.02   237.2 2312.34   254.8 2314.78   271.9 2316.02
   282.3 2315.31   296.8 2315.82   314.6  2321.1   339.5  2332.4   364.4 2347.96
   370.1 2356.12   375.1  2361.5   385.7 2376.58   390.1 2379.64     404 2385.21
#Mann= 5 ,-1 , 0
       0      .1       0   78.64     .06       0  197.48    .045       0
  214.99     .06       0  222.36      .1       0
Bank Sta=197.48,214.99
XS Rating Curve= 0 ,0
Exp/Cntr=0.3,0.1
LCMann Table=0

Chan Stop Cuts=-1
Use User Specified Reach Order=0
Composite Channel Slope=5